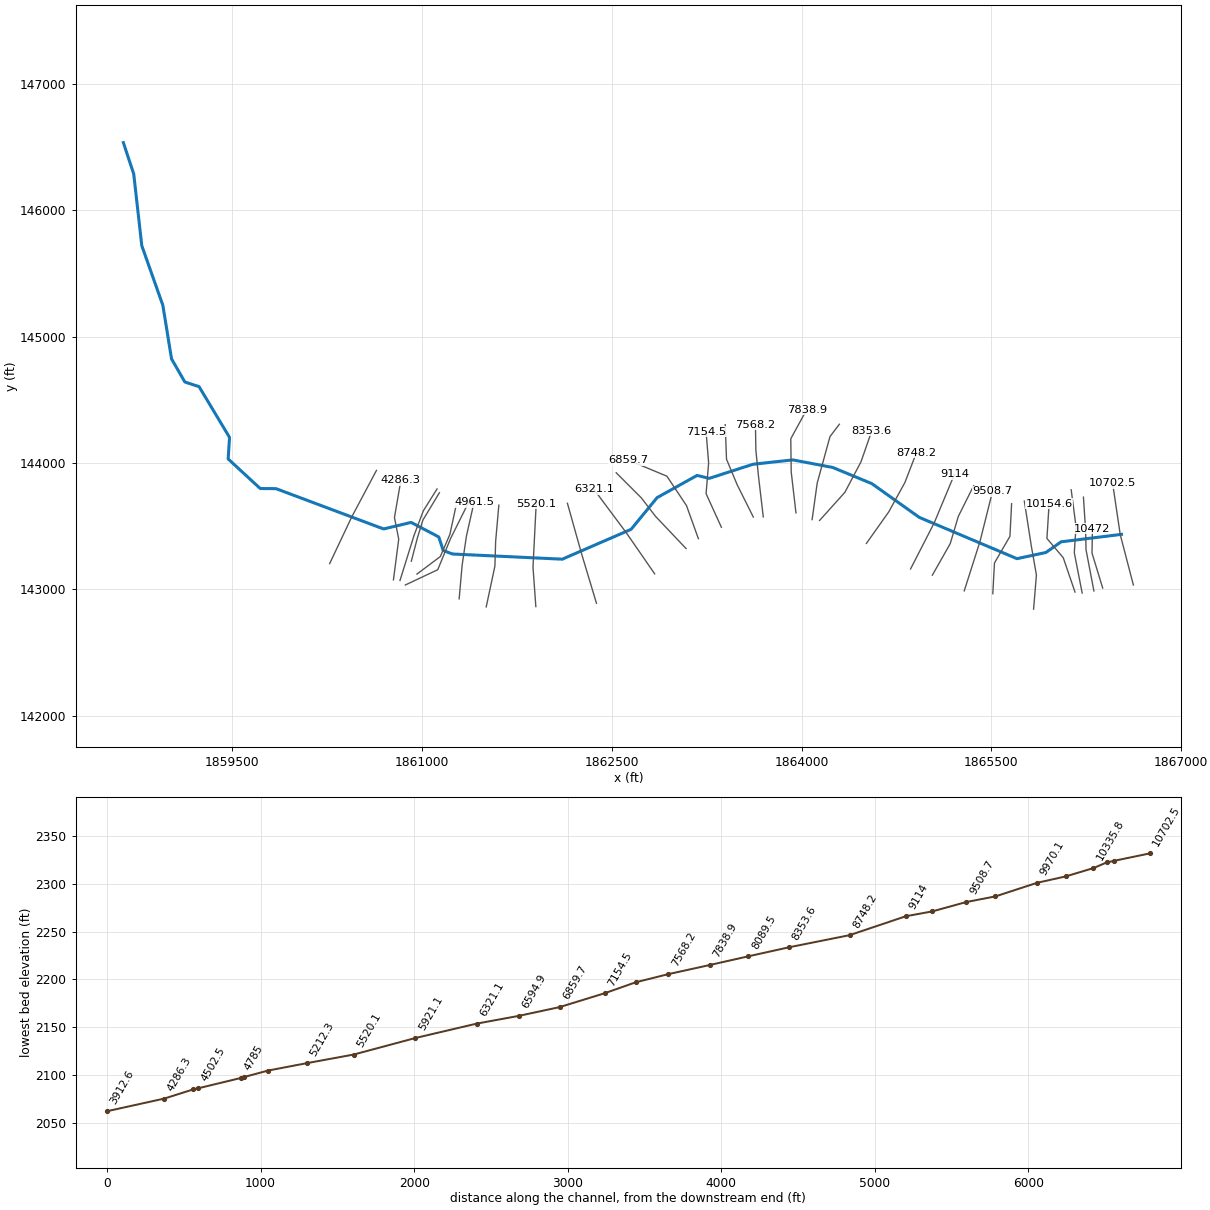
--- Leftwich Branch.prj (project) ---

Proj Title=Leftwich Branch
Current Plan=p01
Default Exp/Contr=0,0
English Units
Geom File=g01
Flow File=f01
Plan File=p01
BEGIN DESCRIPTION:
END DESCRIPTION:
DSS Export Rating Curves= 0
DSS Export Rating Curve Sorted= 0
DSS Export Volume Flow Curves= 0
DXF OffsetX= 0
DXF OffsetY= 0
DXF ScaleX= 0
DXF ScaleY= 0

--- Leftwich Branch.p01 (plan) ---

Plan Title=Floodplain
Program Version=4.00
Geom File=g01
Flow File=f01
K Sum by GR=0
Std Step Tol=0.01
Critical Tol=0.01
Num of Std Step Trials=20
Max Error Tol=0.3
Flow Tol Ratio=0.001
Split Flow NTrial=30
Split Flow Tol=0.02
Split Flow Ratio=0.02
Log Output Level=0
Friction Slope Method=1
Unsteady Friction Slope Method=2
Unsteady Bridges Friction Slope Method=1
Global Log Level=0
CheckData=False
Run HTab=0
Run UNet=0
Run PostProcess=0
UNET Theta=0
UNET Theta Warmup=0
UNET ZTol=0
UNET ZSATol=0
UNET MxIter=0
UNET MaxInSteps=0
UNET DtIC=0
UNET DtMin=0
UNET MaxCRTS=0
UNET WFStab=0
UNET SFStab=0
UNET WFX=0
UNET SFX=0
UNET DSS MLevel=0
UNET DZMax Abort=0
UNET Convert EG Bridges=0
UNET Use Existing IB Tables=0
UNET Froude Limit=0
UNET Froude Power=0
Write IC File=0
Echo Input=False
Echo Output=False
Write Detailed=0

--- Leftwich Branch.f01 (steady flow) ---

Flow Title=NFF Regression Equation
Program Version=4.00
Number of Profiles=1
Profile Names=P100yr
River Rch & RM=Leftwich Branch,Main      ,10702.5
603.8149
River Rch & RM=Leftwich Branch,Main      ,9285.7
660.9455
River Rch & RM=Leftwich Branch,Main      ,8089.5
722.6460
River Rch & RM=Leftwich Branch,Main      ,6859.7
771.6020
River Rch & RM=Leftwich Branch,Main      ,5520.1
845.6526
River Rch & RM=Leftwich Branch,Main      ,3202.8
933.6938
River Rch & RM=Leftwich Branch,Main      ,299.8
1027.343
Boundary for River Rch & Prof#=Leftwich Branch,Main      ,1
Up Type=0
Dn Type=3
Dn Slope=0.017798

--- Leftwich Branch.g01 (geometry) ---

Geom Title=USGS 10m DEM
Program Version=4.00

River Reach=Leftwich Branch ,Main
Reach XY= 30
      1866529.27      143435.824     1866051.928      143376.706
     1865931.806      143292.433     1865703.014      143243.577
     1864931.212      143569.782     1864555.539      143836.874
      1864246.33      143964.737     1863929.989      144024.483
     1863615.534      143989.893      1863269.77      143878.404
      1863174.04      143901.846     1862857.797      143726.038
     1862652.045      143475.445     1862108.039      143239.604
     1861240.144      143280.484     1861166.561      143308.155
     1861131.633        143415.3     1860913.111       143530.16
     1860695.509       143478.59     1859844.722      143797.228
      1859720.07      143798.076      1859466.62       144032.03
     1859477.312      144202.464     1859236.439      144603.709
     1859124.377      144640.326     1859018.837      144823.198
     1858950.285      145246.454     1858783.603      145718.623
     1858720.105      146284.154      1858638.05      146533.202

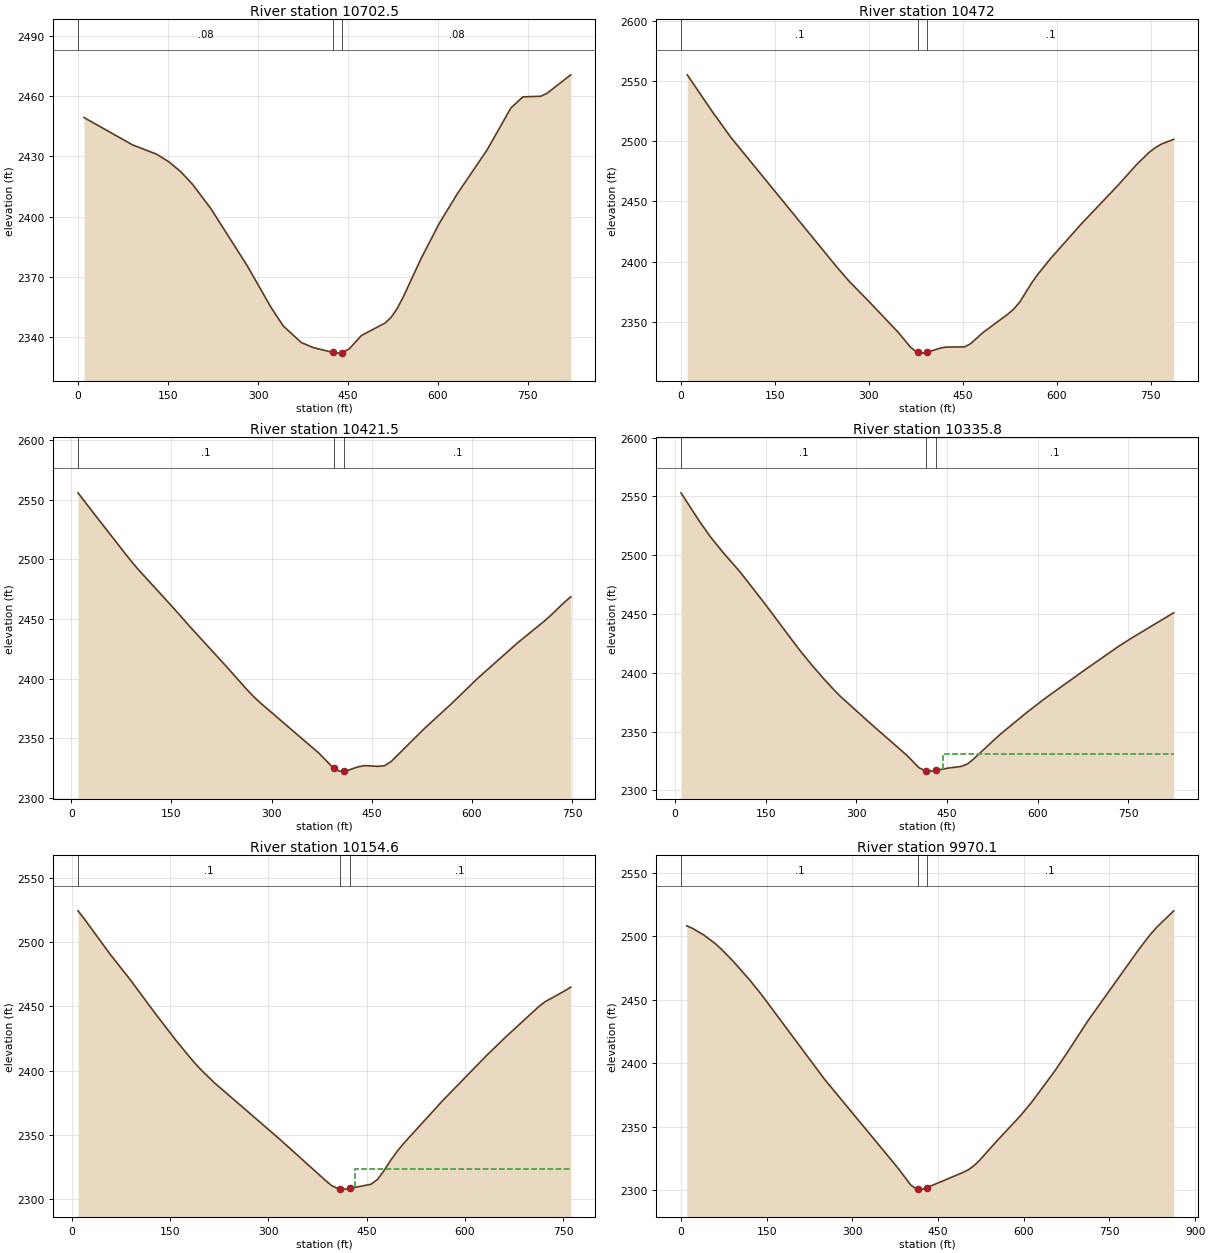
Type RM Length L Ch R = 1 ,10702.5 ,236.7,230.6,226.9
XS GIS Cut Line= 3
     1866623.401      143035.284     1866519.378      143434.359
     1866459.441      143838.929
#Sta/Elev= 30
    10.1 2449.45    90.5 2435.86   130.8 2431.17   150.9 2427.46     171 2422.49
   191.1    2416   221.3 2404.01   281.6 2375.61   321.9 2354.49     342 2345.33
   372.2 2337.01   392.3 2334.47   424.9 2332.07   432.4 2331.72   439.9 2331.91
   452.3  2333.9   472.3 2340.51   512.2 2346.84   522.1 2349.68   532.1 2354.05
   542.1 2359.79     572 2379.11   601.9 2396.41   631.9 2411.23   681.7  2433.2
   721.6 2454.28   741.6  2459.8   771.5 2460.13   781.5 2461.54   821.4 2470.82
#Mann= 3 , 0 , 0
       0     .08       0   424.9    .045       0   439.9     .08       0
Bank Sta=424.9,439.9
XS Rating Curve= 0 ,0
Exp/Cntr=0.3,0.1

Type RM Length L Ch R = 1 ,10472   ,49.6,50.5,51.3
XS GIS Cut Line= 3
      1866380.87      143011.363     1866296.351       143287.81
     1866299.731      143480.375
#Sta/Elev= 30
      10 2554.99    49.8 2524.59    79.7 2503.02   249.2  2395.2   269.1 2383.28
   298.7 2367.63   346.9 2341.19   366.1 2329.11   375.7 2325.05   377.9 2324.82
   385.4 2324.04   392.9 2324.79   414.3 2328.28   423.9 2329.07   452.8 2329.24
   462.4 2331.93   481.7 2340.98     521 2356.11   530.8 2360.44   540.7 2366.43
   560.3 2382.73   570.2  2389.9   589.9 2402.52     639 2431.29     698 2463.59
   727.5 2480.69   747.2 2490.64     757 2494.49   766.9 2497.54   786.5  2501.5
#Mann= 3 , 0 , 0
       0      .1       0   377.9    .045       0   392.9      .1       0
Bank Sta=377.9,392.9
XS Rating Curve= 0 ,0
Exp/Cntr=0.3,0.1

Type RM Length L Ch R = 1 ,10421.5 ,87.6,85.7,83.8
XS GIS Cut Line= 4
      1866311.34      142988.441     1866248.941      143314.946
     1866246.039       143461.51     1866228.625       143729.97
#Sta/Elev= 30
    10.1 2555.99    30.2 2541.24    80.6  2505.1    90.7 2497.97   100.7 2491.34
   151.1 2460.47   181.3 2441.36   231.7  2410.5   261.9 2391.44     272 2385.47
     282 2380.14   371.5 2337.02   391.1 2325.63   393.3 2324.87   400.8 2322.27
   408.3 2322.28   410.6 2322.28   430.1 2325.98   439.9  2326.9   459.5 2326.25
   469.2 2326.85     479 2330.34   528.8 2358.08   568.7 2378.55   608.5  2400.2
   668.3    2430   708.2 2448.21   718.1  2453.1   738.1 2463.95     748 2468.68
#Mann= 3 , 0 , 0
    10.1      .1       0   393.3    .045       0   408.3      .1       0
Bank Sta=393.3,408.3
XS Rating Curve= 0 ,0
Exp/Cntr=0.3,0.1

Type RM Length L Ch R = 1 ,10335.8 ,163.7,181.2,198.6
XS GIS Cut Line= 4
     1866218.544      142971.979     1866156.343      143289.807
     1866169.806       143498.48     1866131.731      143788.026
#Sta/Elev= 30
     9.8 2553.04    39.3 2529.64    58.9 2515.32    78.5 2502.88     108 2485.51
   147.2 2459.63   206.1 2419.25   225.7 2406.96   245.3 2395.33     265 2384.34
   274.8 2379.35   323.9 2356.62   383.6 2329.78   403.5 2319.31   413.5 2316.72
   415.9 2316.64   423.4 2316.39   430.9 2317.01   453.3 2319.09   473.2 2320.38
   483.2 2322.29   493.1 2326.35     533 2345.42     543 2349.85   583.3 2366.85
   613.5 2378.78     684  2404.7   734.4 2422.71   754.5  2429.3     825 2451.08
#Mann= 3 , 0 , 0
     9.8      .1       0   415.9    .045       0   430.9      .1       0
#XS Ineff= 2 , 0
                          442.44         2331.13
Permanent Ineff=
       F       F
Bank Sta=415.9,430.9
XS Rating Curve= 0 ,0
Exp/Cntr=0.3,0.1

Type RM Length L Ch R = 1 ,10154.6 ,196.5,184.5,172.5
XS GIS Cut Line= 4
     1866161.873      142979.734        1866069.      143251.096
      1865939.85      143403.465     1865957.263      143677.729
#Sta/Elev= 30
     9.9 2524.54    19.8    2518    59.3 2490.39      89 2471.21   128.6  2443.9
   158.2 2424.28     178 2411.87   187.9 2405.93   197.8 2400.49   217.6 2390.64
   316.8 2346.87   386.7  2314.7   396.7 2310.39   406.7 2307.95   409.1 2307.88
   416.6 2307.65   424.1 2308.18   456.6 2311.44   466.6 2315.21   476.6 2322.11
   486.6 2330.01   496.4 2336.97   506.2 2343.09   565.1 2376.15   633.8 2412.25
   663.2 2426.71   712.3 2449.78   722.1 2453.67   751.6 2461.98   761.4  2465.1
#Mann= 3 , 0 , 0
     9.9      .1       0   409.1    .045       0   424.1      .1       0
#XS Ineff= 2 , 0
                          432.22         2323.35
Permanent Ineff=
       F       F
Bank Sta=409.1,424.1
XS Rating Curve= 0 ,0
Exp/Cntr=0.3,0.1

Type RM Length L Ch R = 1 ,9970.1  ,289,272.6,256.3
XS GIS Cut Line= 4
     1865834.539      142844.752     1865856.796      143114.791
     1865816.408      143343.658     1865761.345      143698.517
#Sta/Elev= 30
      10 2508.31    20.1 2506.28    40.1 2501.02    60.2 2494.18    70.2 2490.06
    90.3  2480.9   120.4 2465.58   140.5 2454.39   250.9 2387.72     372  2321.9
   382.1  2316.3   402.3  2304.2   412.4 2301.16     415 2301.13   422.5 2301.06
     430 2302.17   493.3 2314.12   503.4 2316.38   513.3 2319.71   523.3 2324.05
   553.2 2339.13   593.1 2358.28   613.1 2369.03     653 2393.24   672.9 2406.36
   712.8 2433.88   802.6 2490.45   822.6 2502.02   832.5 2507.03   862.5 2520.06
#Mann= 3 , 0 , 0
       0      .1       0     415    .045       0     430      .1       0
Bank Sta=415,430
XS Rating Curve= 0 ,0
Exp/Cntr=0.3,0.1

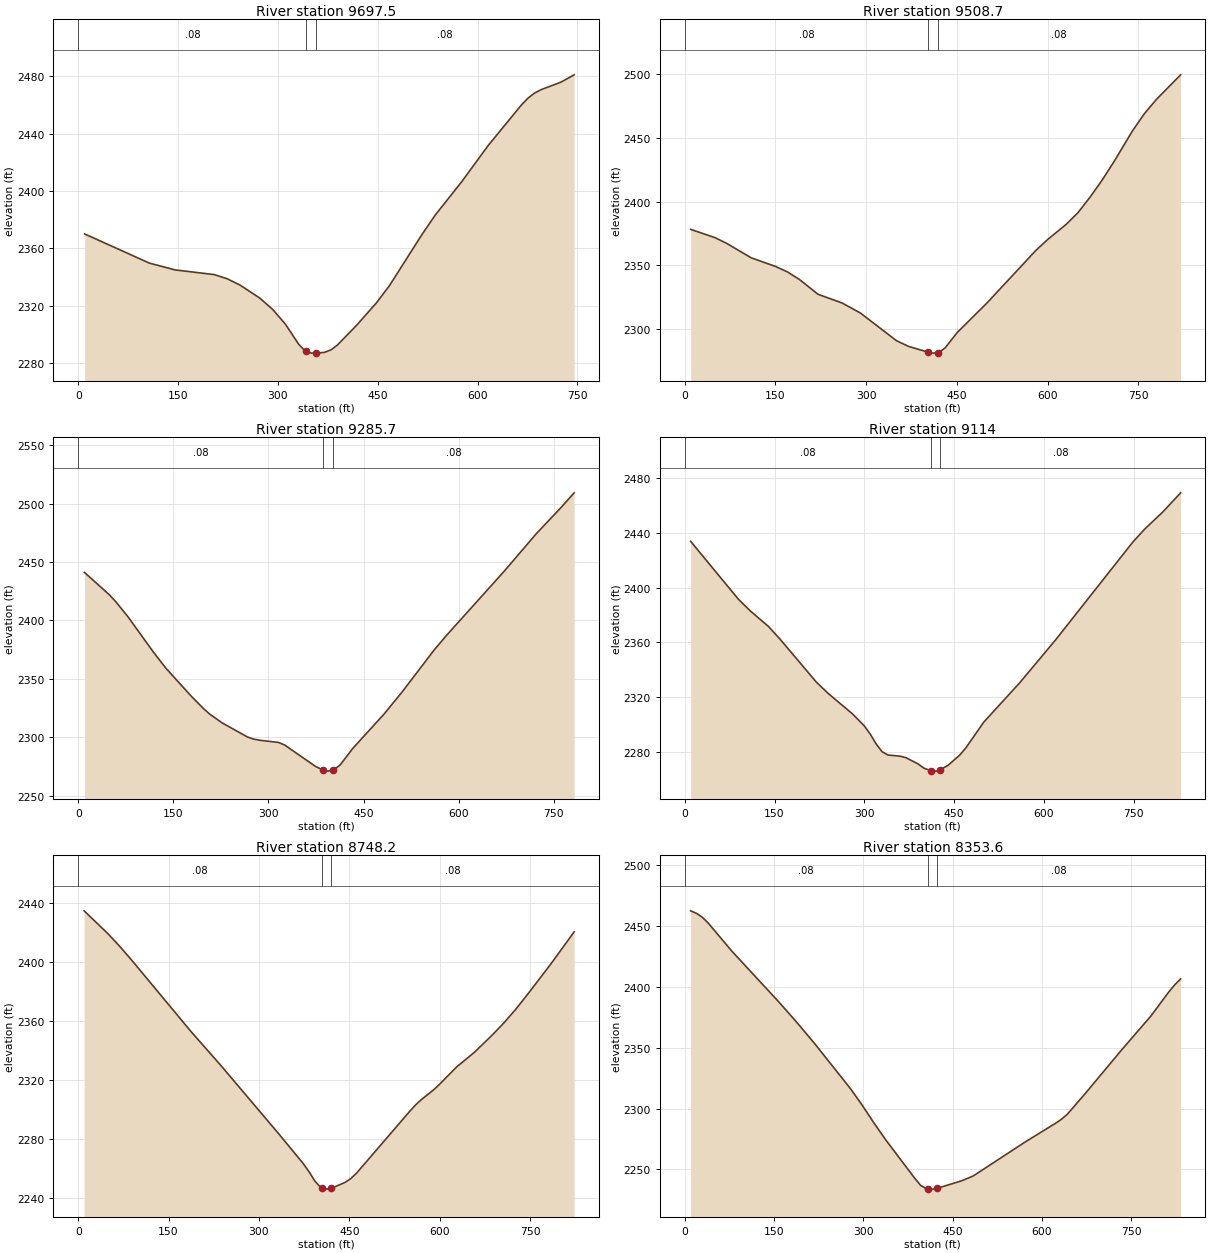
Type RM Length L Ch R = 1 ,9697.5  ,183.9,188.8,195.1
XS GIS Cut Line= 4
      1865511.92      142966.719     1865525.096      143209.532
     1865647.444      143420.347      1865660.62      143678.219
#Sta/Elev= 30
     9.7 2369.97     107  2349.6   145.9 2344.85   204.3 2341.61   223.7 2338.72
   243.2 2334.28   272.4 2325.35   291.9 2317.43   311.4 2306.97   330.9 2293.23
   340.7 2288.38   342.9 2288.02   350.4 2286.81   357.9 2286.86   369.9 2287.33
   379.7 2289.08   389.4 2292.43   418.7 2306.45   447.9 2321.81   467.4 2333.75
   516.7 2369.73   536.6 2383.26   576.3 2406.49     616  2431.7   665.7 2459.88
   675.6 2464.64   685.5 2468.24   695.5 2470.66   725.3  2475.9   745.1 2480.99
#Mann= 3 , 0 , 0
       0     .08       0   342.9    .045       0   357.9     .08       0
Bank Sta=342.9,357.9
XS Rating Curve= 0 ,0
Exp/Cntr=0.3,0.1

Type RM Length L Ch R = 1 ,9508.7  ,222.5,223,222
XS GIS Cut Line= 3
      1865286.05      142988.818     1865410.868      143379.902
     1865510.143         143777.
#Sta/Elev= 30
      10 2378.16    50.1  2371.7    70.1 2367.02   110.1  2355.8   150.2 2349.05
   170.2 2344.69   190.2 2338.64   220.3 2327.21   260.3 2320.32   290.4 2312.49
   350.4 2290.63   370.5 2286.17     403 2281.63   410.5 2280.95     418 2281.38
   420.5 2281.52   430.5 2285.05   450.5 2297.13   500.4 2320.69   580.2 2361.49
   600.2 2370.29   630.2 2381.94   650.1 2391.29   670.1  2403.5   690.1 2416.88
     710 2431.65     740 2455.38   759.9 2469.07   779.9 2480.35   819.8  2499.6
#Mann= 3 , 0 , 0
       0     .08       0     403    .045       0     418     .08       0
Bank Sta=403,418
XS Rating Curve= 0 ,0
Exp/Cntr=0.3,0.1

Type RM Length L Ch R = 1 ,9285.7  ,176,171.8,169.4
XS GIS Cut Line= 4
     1865034.005      143113.243     1865175.364      143362.304
     1865239.312      143577.709     1865360.477      143820.038
#Sta/Elev= 30
     9.9 2441.13    49.4 2421.82    59.3 2416.03      79  2402.8   118.5    2373
   138.3 2359.16   177.8 2335.51   197.5 2324.64   207.4  2319.9   227.1 2312.32
   266.6 2300.43   276.5 2298.51   286.4 2297.53   315.7 2295.68   325.5 2293.46
   374.3 2275.12   386.3 2272.03   393.8 2271.12   401.3 2272.05   403.6 2272.34
   413.4 2276.67   432.9 2290.53   481.8 2319.65   511.1 2339.11   561.2 2374.73
   581.3 2387.58   671.6 2442.06   721.8 2473.93   761.9 2496.97     782  2509.2
#Mann= 3 , 0 , 0
       0     .08       0   386.3    .045       0   401.3     .08       0
Bank Sta=386.3,401.3
XS Rating Curve= 0 ,0
Exp/Cntr=0.3,0.1

Type RM Length L Ch R = 1 ,9114    ,367,365.8,362.6
XS GIS Cut Line= 3
     1864861.768      143162.275     1865048.727      143526.684
     1865209.776      143913.025
#Sta/Elev= 30
      10 2433.68    89.9 2391.35   109.9 2382.81   139.9 2371.59   159.8 2362.04
   219.8 2331.02   239.7 2322.72   279.7 2308.03   299.7 2299.18   309.7 2293.22
   319.7 2285.91   329.7 2280.18   339.6 2277.81   359.6 2276.98   369.6 2275.85
   389.6 2271.35   399.6 2268.21     412 2266.18   419.5 2266.07     427 2267.15
   439.5  2270.2   459.4 2277.83   469.4 2282.96   499.3 2301.75   559.1 2330.35
   618.9 2361.57   748.4 2433.19   768.3  2442.7   798.2 2455.03   828.1 2469.06
#Mann= 3 , 0 , 0
       0     .08       0     412    .045       0     427     .08       0
Bank Sta=412,427
XS Rating Curve= 0 ,0
Exp/Cntr=0.3,0.1

Type RM Length L Ch R = 1 ,8748.2  ,394.3,394.6,394.8
XS GIS Cut Line= 4
      1864512.67      143364.395     1864688.901      143612.913
     1864816.797      143845.146     1864908.171       144081.57
#Sta/Elev= 30
     9.8 2434.75    49.1 2419.39    68.8 2410.76    88.5 2401.49   186.7 2353.28
   235.9 2330.49   334.1  2283.2   373.4 2263.69   383.2 2258.12     393  2251.7
   402.9 2247.31   405.2 2247.08   412.7 2246.32   420.2 2246.88   442.1  2250.7
     452 2253.27   461.8 2257.02   550.1 2298.89     560 2303.29   569.8 2306.99
   589.3  2313.3     599 2316.97   628.3  2329.1   657.5 2338.87   686.8 2350.45
   706.3 2358.69   725.8 2367.82   745.3  2377.8   784.3  2398.6   823.3 2420.52
#Mann= 3 , 0 , 0
       0     .08       0   405.2    .045       0   420.2     .08       0
Bank Sta=405.2,420.2
XS Rating Curve= 0 ,0
Exp/Cntr=0.3,0.1

Type RM Length L Ch R = 1 ,8353.6  ,259.2,264.1,269
XS GIS Cut Line= 4
      1864142.53      143545.928     1864342.235      143767.735
     1864470.131      144010.065     1864555.731      144255.998
#Sta/Elev= 30
     9.9 2462.67    19.9  2460.6    29.8  2457.3    39.8 2452.45    79.6  2429.3
   159.2 2387.11     189 2370.51   218.9 2353.04   278.6 2316.24   298.5 2302.48
     318 2287.99   337.6 2274.25   386.5 2242.52   396.3 2236.72   406.1 2233.95
   408.4 2233.88   415.9 2233.65   423.4 2234.21   464.8 2240.45   484.4 2244.43
   572.5 2272.65   622.6 2287.77   632.6 2291.08   642.6 2295.26   672.6 2312.22
   732.7 2347.57   782.8 2375.98   812.8 2395.75   822.9 2401.73   832.9 2406.67
#Mann= 3 , 0 , 0
       0     .08       0   408.4    .045       0   423.4     .08       0
Bank Sta=408.4,423.4
XS Rating Curve= 0 ,0
Exp/Cntr=0.3,0.1

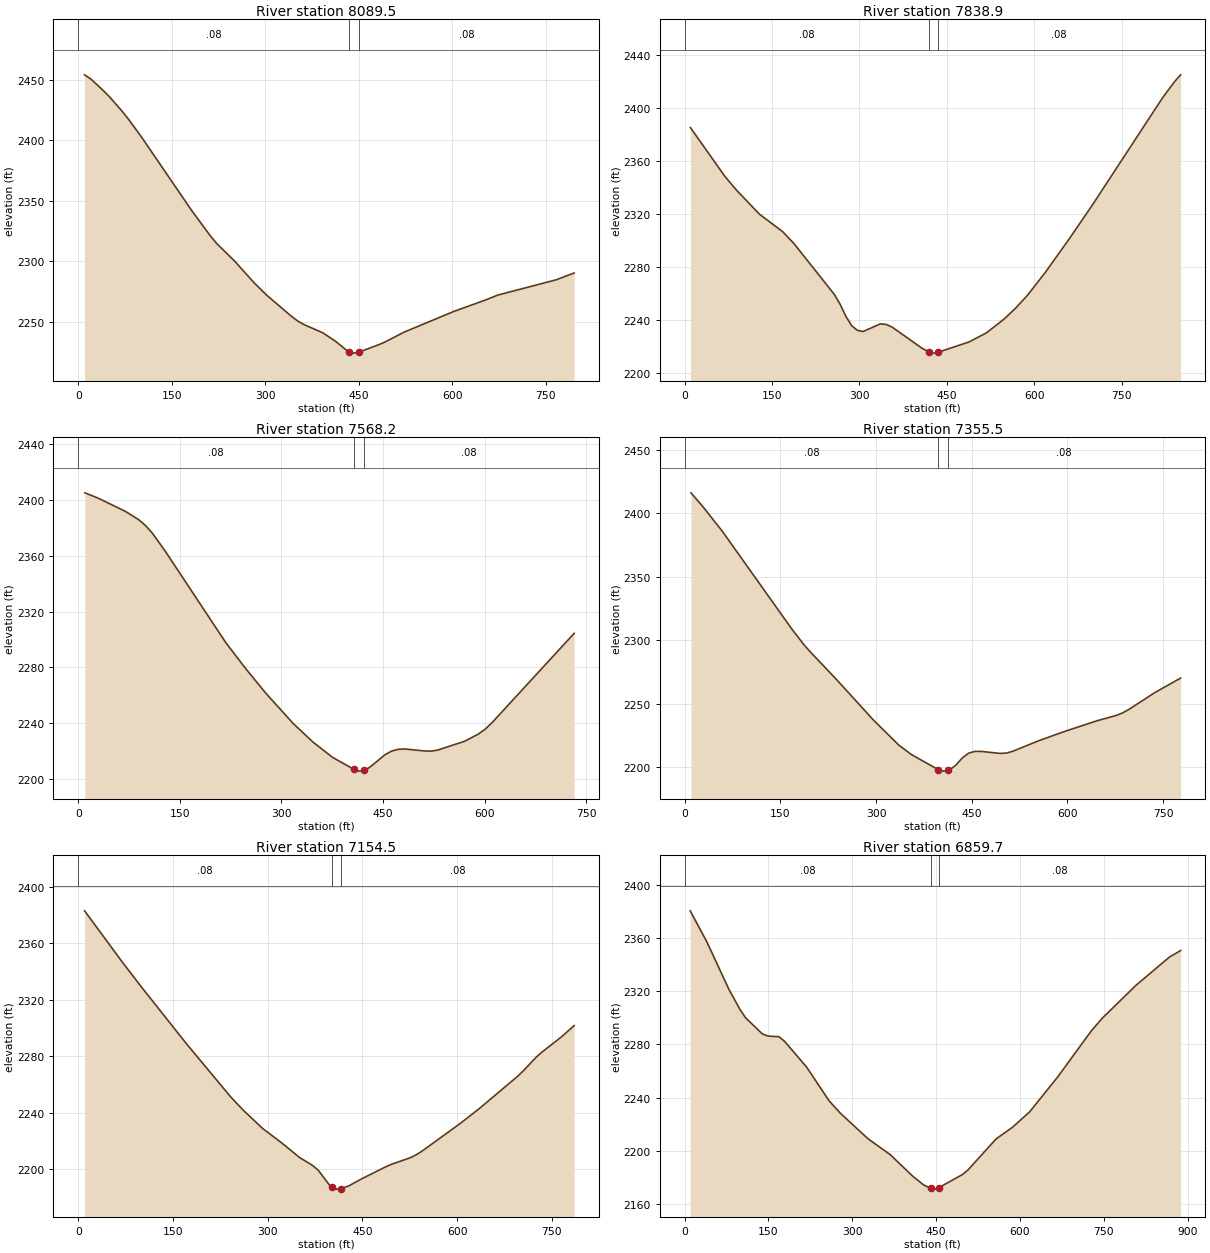
Type RM Length L Ch R = 1 ,8089.5  ,244.2,250.6,257
XS GIS Cut Line= 4
     1864083.411      143552.543     1864123.799      143841.992
      1864224.77      144208.853     1864298.815      144306.458
#Sta/Elev= 30
    10.1 2453.98    20.2 2450.59    40.3 2440.97    50.4 2435.72    70.5 2423.85
    80.6 2417.35   100.8 2403.15   181.4  2342.4   211.6 2321.25   221.7 2314.96
   251.9 2299.66   282.2 2282.23   302.3 2272.08   342.3 2254.48   352.3 2250.68
   362.3 2247.74   392.4 2240.98   412.4 2234.12   432.4 2225.74     435 2225.35
   442.5 2224.24     450 2225.02   482.5  2231.3   492.5 2233.55   522.6 2241.56
   602.7 2258.73   652.7 2268.01   672.8 2272.15     767 2284.85   795.3 2290.41
#Mann= 3 , 0 , 0
       0     .08       0     435    .045       0     450     .08       0
Bank Sta=435,450
XS Rating Curve= 0 ,0
Exp/Cntr=0.3,0.1

Type RM Length L Ch R = 1 ,7838.9  ,268.8,270.7,272.6
XS GIS Cut Line= 4
     1863955.737      143605.501     1863918.157      143929.289
     1863914.792      144191.813     1864040.929      144422.275
#Sta/Elev= 30
     9.9 2385.36    69.1 2348.51    88.9  2338.2   128.4    2320   167.9 2306.96
   187.7 2297.78   256.8 2259.53   266.7 2252.15   276.6 2242.99   286.5 2235.91
   296.3 2232.38   306.2  2231.5   336.1 2237.27   346.2 2236.79   356.3 2234.73
   406.7 2219.07   419.4 2215.89   426.9 2215.17   434.4 2215.75   487.5 2223.51
   517.8 2230.42   548.1 2240.83   568.3 2249.21   588.5  2258.9   618.8 2275.99
   659.2 2300.87   699.7 2326.92   820.9 2408.31   841.1 2420.19   851.2 2425.19
#Mann= 3 , 0 , 0
       0     .08       0   419.4    .045       0   434.4     .08       0
Bank Sta=419.4,434.4
XS Rating Curve= 0 ,0
Exp/Cntr=0.3,0.1

Type RM Length L Ch R = 1 ,7568.2  ,206,212.7,219.4
XS GIS Cut Line= 4
      1863697.25        143573.9     1863658.999      143898.997
     1863638.805      144100.939     1863635.439       144302.88
#Sta/Elev= 30
     9.9 2405.16    29.8 2401.27    69.4 2391.93    89.3 2385.94    99.2 2381.77
   109.1  2376.5     129 2362.97   218.2 2297.56     248  2278.7   277.7 2261.09
   317.4 2239.79   346.7 2226.43   375.7 2215.44   406.8 2207.01   414.3 2205.61
   421.8 2206.11     424 2206.25   433.6 2209.54     453  2217.4   462.6 2219.94
   472.3 2221.25     482 2221.52     511 2220.09   520.6 2219.94   530.3 2220.64
   570.7 2227.04   590.9 2232.21     601 2235.72   611.1 2240.37   732.3 2304.41
#Mann= 3 , 0 , 0
       0     .08       0   406.8    .045       0   421.8     .08       0
Bank Sta=406.8,421.8
XS Rating Curve= 0 ,0
Exp/Cntr=0.3,0.1

Type RM Length L Ch R = 1 ,7355.5  ,211.8,200.9,190.1
XS GIS Cut Line= 4
     1863618.611      143572.525     1863490.714      143828.318
     1863406.572      144030.259     1863396.475       144302.88
#Sta/Elev= 30
     9.9 2416.03    29.6 2404.54    59.2 2385.66   167.6 2309.17   187.4 2296.27
   197.2 2290.76   236.7 2269.89   295.9 2237.31   335.7 2217.58   355.6 2210.08
   397.8 2198.24   405.3 2197.08   412.8 2197.75   415.3 2197.97   425.2 2201.81
   435.1 2207.36   445.1 2211.18     455 2212.61     465 2212.59   494.8    2211
   504.8 2211.31   514.9 2212.79   555.3 2221.04   595.7  2228.3   646.2 2236.65
   676.5 2240.86   686.6 2242.88   696.7 2245.67   737.1 2258.86   777.6  2270.3
#Mann= 3 , 0 , 0
       0     .08       0   397.8    .045       0   412.8     .08       0
Bank Sta=397.8,412.8
XS Rating Curve= 0 ,0
Exp/Cntr=0.3,0.1

Type RM Length L Ch R = 1 ,7154.5  ,279.4,294.8,310.3
XS GIS Cut Line= 4
     1863366.184      143491.749     1863245.019      143757.638
     1863265.213      143999.968     1863245.019      144249.029
#Sta/Elev= 30
    10.1 2382.97    70.5 2346.23   100.8  2328.6   171.3  2288.8   241.8 2250.88
     262 2241.35   292.2 2228.61   321.4 2218.74   350.6 2208.07     370 2202.82
   379.7 2199.28   399.2 2187.77   401.4  2187.3   408.9  2185.7   416.4 2186.01
   428.4 2188.01   447.8 2192.77   486.7  2201.5   496.5 2203.39   525.6 2207.92
   535.4 2210.07   545.4 2212.97   605.3  2232.4   635.3 2242.91   695.3 2265.52
   705.3 2269.82   725.3 2279.32   735.3 2283.22   765.3  2293.7   785.2 2301.64
#Mann= 3 , 0 , 0
       0     .08       0   401.4    .045       0   416.4     .08       0
Bank Sta=401.4,416.4
XS Rating Curve= 0 ,0
Exp/Cntr=0.3,0.1

Type RM Length L Ch R = 1 ,6859.7  ,263.4,264.8,266.3
XS GIS Cut Line= 4
     1863184.189      143401.713     1863090.197      143663.399
     1862935.375      143895.632     1862630.387      144022.912
#Sta/Elev= 30
     9.9 2380.56    39.7  2357.2    79.4  2321.3    99.3 2306.13   109.2 2299.99
     139 2287.98     149 2286.32   168.8 2285.82   178.7 2282.41   218.5 2262.85
   258.2 2237.79   278.1 2228.47   327.9 2209.14   367.8 2197.12   407.6 2181.09
   427.6 2174.37     440 2171.74   447.5 2171.15     455  2172.3   497.4 2182.19
   507.3 2185.69   557.2 2208.85   587.2 2217.87   617.3 2229.29   667.3 2255.38
   727.4 2290.02   747.4 2299.78   807.5 2324.44   867.6 2345.77   887.6 2350.67
#Mann= 3 , 0 , 0
       0     .08       0     440    .045       0     455     .08       0
Bank Sta=440,455
XS Rating Curve= 0 ,0
Exp/Cntr=0.3,0.1

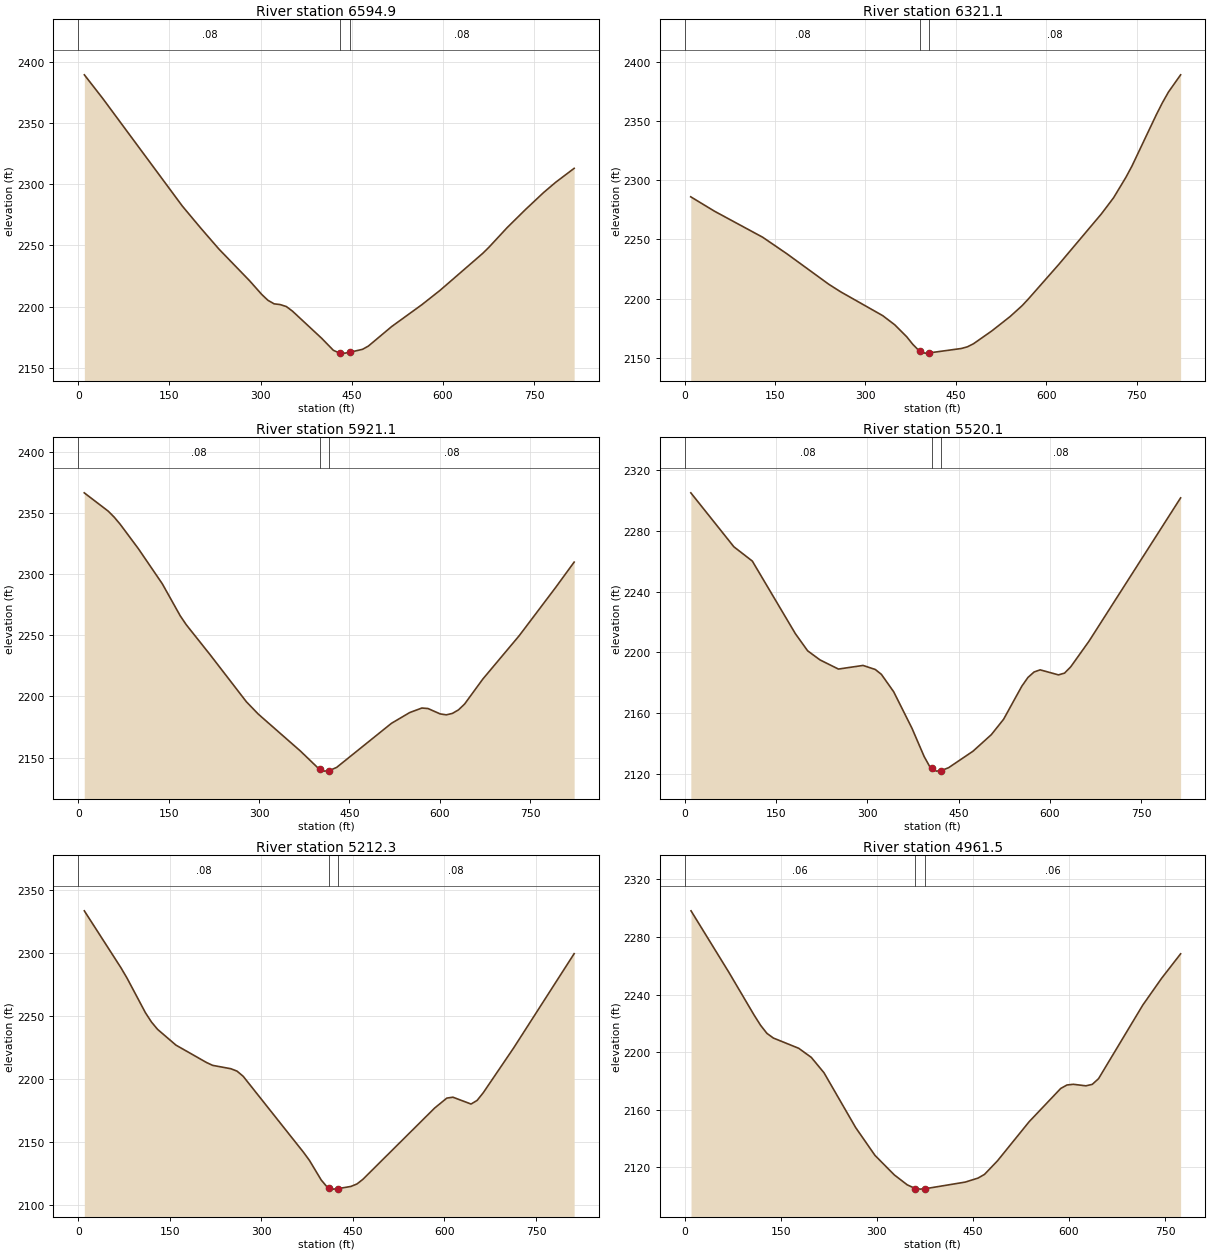
Type RM Length L Ch R = 1 ,6594.9  ,274.8,273.8,273.6
XS GIS Cut Line= 4
     1863086.831      143323.464     1862844.501      143579.256
     1862733.434      143723.981     1862534.858      143922.557
#Sta/Elev= 30
    10.1  2389.3    40.3 2370.04   171.1  2282.2   201.3 2264.25   231.5 2246.95
   281.9 2221.09     302 2209.85   312.1 2205.12   322.2 2202.27   332.2 2201.65
   342.3 2200.05   352.4 2196.28   400.4 2174.12   419.6 2164.33   429.2 2162.14
   431.3 2162.11   438.8 2162.01   446.3 2162.68   467.6 2165.12   477.2 2167.78
   515.6 2183.75   564.9 2201.47     595 2213.25   665.2 2243.46   675.2 2248.34
   705.3 2264.46   735.4  2279.2   765.5 2293.22   785.5 2301.65   815.6 2312.92
#Mann= 3 , 0 , 0
       0     .08       0   431.3    .045       0   446.3     .08       0
Bank Sta=431.3,446.3
XS Rating Curve= 0 ,0
Exp/Cntr=0.3,0.1

Type RM Length L Ch R = 1 ,6321.1  ,407.5,400,391.3
XS GIS Cut Line= 3
     1862838.741        143123.5     1862612.254       143451.33
     1862358.482      143791.726
#Sta/Elev= 30
      10 2285.99    49.8 2273.73   129.5 2251.81   169.3 2237.98   239.1 2212.12
     259 2205.69   328.7 2185.59   348.7 2177.84   368.6 2167.68   378.5  2161.4
   388.5 2156.23     391 2155.66   398.5 2153.94     406 2154.15   459.1 2157.85
   469.2 2159.28   479.3 2161.86   509.7  2172.7     540 2184.82   560.2 2194.14
   570.3 2199.65   620.9 2228.91   691.6 2271.61   711.8 2285.22   732.1 2302.35
   742.2  2311.9   782.6 2355.23   792.7 2365.37   802.8 2374.46     823 2389.02
#Mann= 3 , 0 , 0
       0     .08       0     391    .045       0     406     .08       0
Bank Sta=391,406
XS Rating Curve= 0 ,0
Exp/Cntr=0.3,0.1

Type RM Length L Ch R = 1 ,5921.1  ,409.3,401,393.2
XS GIS Cut Line= 3
     1862378.451       142891.27     1862260.676      143282.589
     1862148.812      143681.474
#Sta/Elev= 30
      10 2366.57    49.8 2351.58    59.8 2346.63    69.8 2340.75    99.7 2320.95
   139.5 2292.18   169.4 2265.84   179.4 2258.59   219.3 2233.84   279.1 2195.59
     299 2185.44   368.8 2155.27   398.7 2141.09   401.2 2140.54   408.7 2138.88
   416.2 2139.19   428.9 2141.96   519.8 2178.01   550.1 2186.82   570.3 2190.51
   580.4 2190.08   600.6  2185.7   610.7 2184.94   620.8 2186.08     631    2189
   641.1 2193.76   671.4 2214.23     732 2249.84   792.6 2289.41   822.9 2309.89
#Mann= 3 , 0 , 0
       0     .08       0   401.2    .045       0   416.2     .08       0
Bank Sta=401.2,416.2
XS Rating Curve= 0 ,0
Exp/Cntr=0.3,0.1

Type RM Length L Ch R = 1 ,5520.1  ,307.4,307.8,308.1
XS GIS Cut Line= 3
     1861899.131      142864.685     1861876.625      143176.951
     1861901.944      143677.701
#Sta/Elev= 30
    10.1 2305.03    80.8 2269.47   111.1 2260.05   181.8 2212.21     202  2200.9
   222.2 2194.94   252.5 2188.89   292.9 2191.28   313.1 2188.61   323.1 2185.38
   343.2 2173.97   373.2 2149.96   393.3 2131.25   403.3 2124.03   405.9 2123.41
   413.4 2121.63   420.9 2121.93   433.4 2123.88   473.5 2134.75   503.6 2145.66
   523.7 2155.77   553.7  2177.6   563.8 2183.37   573.8 2186.96   583.8 2188.37
   613.9 2185.06   623.9 2186.23     634 2190.35     664 2207.23   814.5 2301.71
#Mann= 3 , 0 , 0
       0     .08       0   405.9    .045       0   420.9     .08       0
Bank Sta=405.9,420.9
XS Rating Curve= 0 ,0
Exp/Cntr=0.3,0.1

Type RM Length L Ch R = 1 ,5212.3  ,253.4,250.8,248.2
XS GIS Cut Line= 4
      1861506.88      142862.395     1861575.612      143185.391
     1861581.239      143379.502     1861606.557      143666.449
#Sta/Elev= 30
      10  2333.5      70 2288.31    80.1 2279.99   110.1 2252.62   120.1 2245.16
   130.1 2239.36   160.1 2226.88   210.1  2213.1   220.2 2210.81   250.2 2208.12
   260.2 2206.22   270.2 2202.17   369.1 2141.78   378.8 2135.37   398.2 2119.73
   407.9 2114.19   410.1 2113.81   417.6 2112.54   425.1 2112.89   446.7 2114.66
   456.5  2116.6   466.2 2120.23     584 2176.94   603.9 2184.81   613.8 2185.54
   643.6  2180.1   653.6 2183.01   663.5 2189.01   713.2 2224.51   812.5 2299.47
#Mann= 3 , 0 , 0
       0     .08       0   410.1    .045       0   425.1     .08       0
Bank Sta=410.1,425.1
XS Rating Curve= 0 ,0
Exp/Cntr=0.3,0.1

Type RM Length L Ch R = 1 ,4961.5  ,162,156.2,150.5
XS GIS Cut Line= 4
     1861292.917      142926.312     1861316.477      143192.202
     1861350.134      143421.069     1861410.716      143690.324
#Sta/Elev= 30
     9.9 2298.18    69.2 2255.33   108.7 2225.53   118.6 2218.61   128.5 2213.02
   138.4 2209.82     178  2202.7   197.7 2196.36   217.5 2185.69   266.9 2147.64
   297.1 2128.29   327.3 2114.73   347.4 2107.85     360 2105.29   367.5 2104.86
     375  2105.1   437.9 2109.74     458 2112.53   468.1 2115.12   488.2 2124.46
   537.7 2151.67     587 2174.77   596.8  2177.2   606.7 2177.68   626.4 2176.62
   636.3 2177.64   646.1  2181.6   715.1 2232.67   744.7 2251.42   774.2 2268.32
#Mann= 3 , 0 , 0
       0     .06       0     360    .045       0     375     .06       0
Bank Sta=360,375
XS Rating Curve= 0 ,0
Exp/Cntr=0.3,0.1

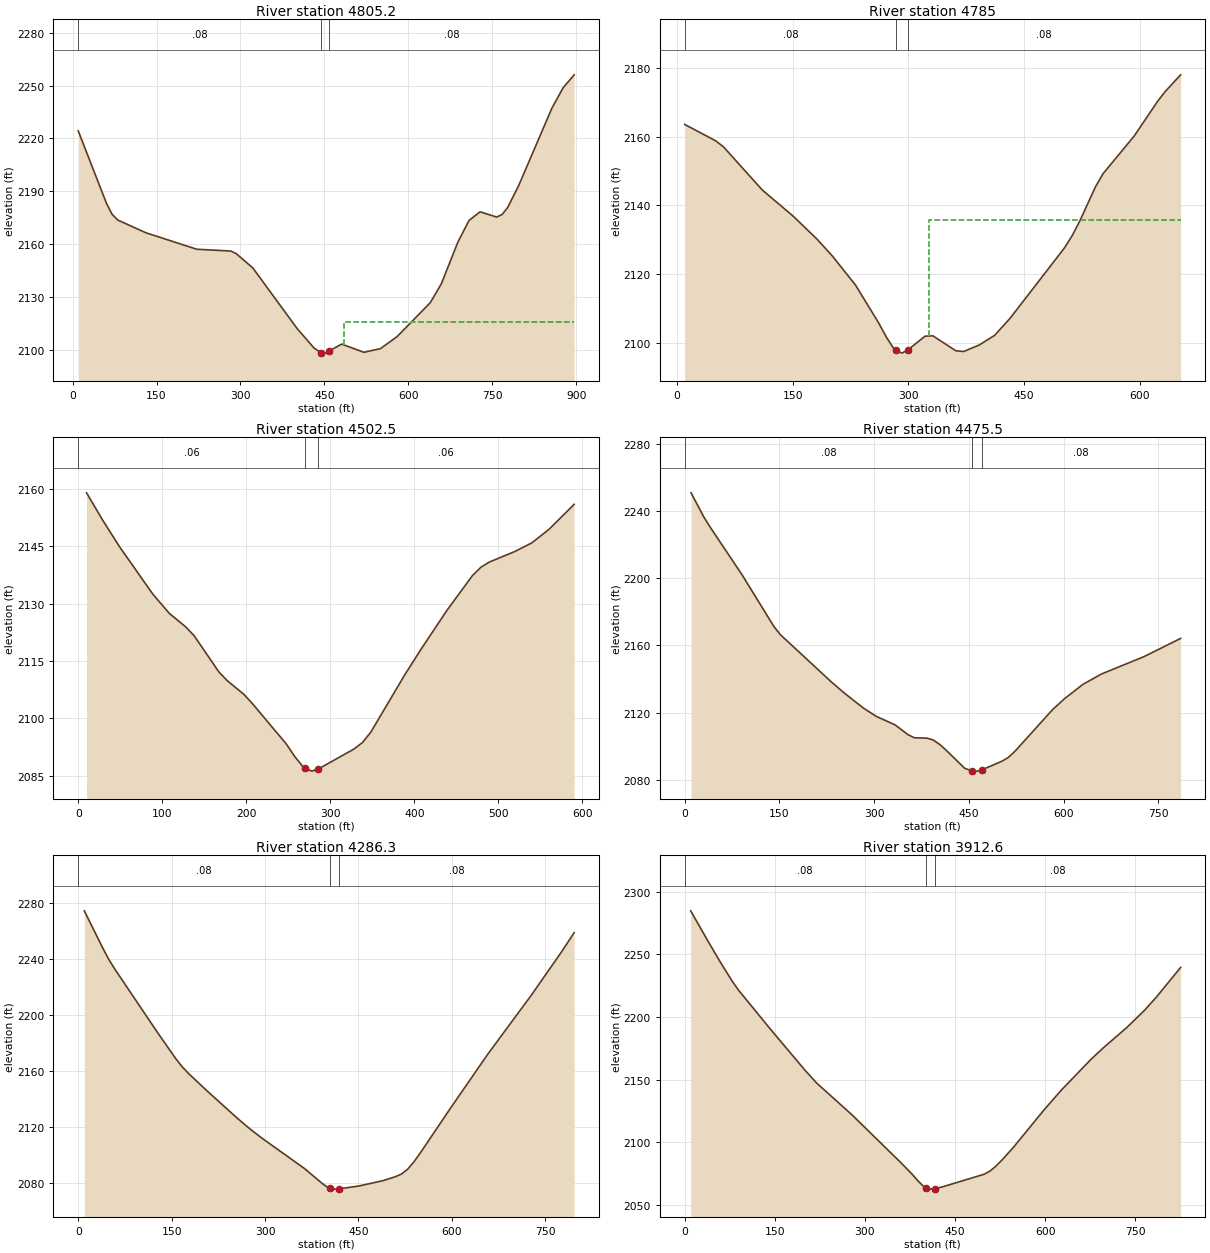
Type RM Length L Ch R = 1 ,4805.2  ,20.2,20.2,21.3
XS GIS Cut Line= 4
     1860867.847      143035.859     1861123.517      143156.216
     1861225.417      143403.686     1861379.715      143713.352
#Sta/Elev= 30
    10.1  2224.3    60.6 2183.13    70.6 2176.94    80.7 2173.67   131.2  2166.4
     222 2157.07   282.6 2156.06   292.5 2154.56   322.2  2146.4   401.5 2111.95
   431.3 2101.07   443.6 2098.39   451.1  2098.1   458.6 2099.31   480.8 2103.24
   520.5 2098.56   550.2 2100.66   579.9  2107.5   639.2 2126.76   658.9 2137.45
   688.6 2161.21   708.4 2173.43   728.1 2178.32   757.8 2175.35   767.7 2176.86
   777.6 2180.86   797.3 2193.37   856.6 2237.26   876.4 2248.67   896.2 2256.09
#Mann= 3 , 0 , 0
    10.1     .08       0   443.6    .045       0   458.6     .08       0
#XS Ineff= 2 , 0
                          484.47         2115.75
Permanent Ineff=
       F       F
Bank Sta=443.6,458.6
XS Rating Curve= 0 ,0
Exp/Cntr=0.3,0.1

Type RM Length L Ch R = 1 ,4785    ,281.5,282.5,282.5
XS GIS Cut Line= 4
     1860959.364      143121.805     1861144.394      143260.896
     1861219.682      143435.717     1861268.172      143661.582
#Sta/Elev= 30
    10.1 2163.53    50.3 2158.77    60.4 2157.01   110.7 2144.49     151 2136.83
   181.2 2130.32   201.3 2125.38   231.5 2116.89   261.5  2105.9   271.6 2101.74
   281.6 2098.25   284.1 2097.97   291.6 2097.13   299.1 2098.02   321.6 2102.05
   331.7 2102.16   361.7 2097.79   371.7 2097.61   391.8 2099.49   411.8  2102.3
   431.9 2107.27   502.2 2127.66   512.2 2131.21   522.3 2135.57   542.4  2145.4
   552.4 2149.26   592.6 2160.15   622.7 2170.15   632.7 2173.05   652.8 2177.93
#Mann= 3 , 0 , 0
    10.1     .08       0   284.1    .045       0   299.1     .08       0
#XS Ineff= 2 , 0
                          326.37         2135.72
Permanent Ineff=
       F       F
Bank Sta=284.1,299.1
XS Rating Curve= 0 ,0
Exp/Cntr=0.3,0.1

Type RM Length L Ch R = 1 ,4502.5  ,28.4,26.9,25.5
XS GIS Cut Line= 4
     1860914.701       143223.89     1860961.916      143405.092
     1861006.578      143549.288     1861136.737      143764.943
#Sta/Elev= 30
     9.9 2159.03    29.6 2151.71    49.3 2144.89    88.7 2132.54   108.4 2127.48
   128.1 2123.91     138 2121.61   167.5 2112.12   177.4 2109.86   197.3 2106.25
   207.4 2103.83   247.6  2093.3   257.7    2090   267.8 2087.25   270.3 2086.99
   277.8 2086.19   285.3  2086.7   328.1 2091.97   338.2 2093.67   348.3 2096.44
   388.6 2111.42   408.7 2118.36     439 2128.35   469.2  2137.4   479.3 2139.58
   489.3 2140.92   519.6 2143.68   539.7 2145.93   559.9 2149.42   590.1 2156.02
#Mann= 3 , 0 , 0
       0     .06       0   270.3    .045       0   285.3     .06       0
Bank Sta=270.3,285.3
XS Rating Curve= 0 ,0
Exp/Cntr=0.3,0.1

Type RM Length L Ch R = 1 ,4475.5  ,176,189.2,202.4
XS GIS Cut Line= 4
     1860825.086      143071.037     1860936.154        143427.8
     1861010.199      143623.011     1861117.901      143794.661
#Sta/Elev= 30
    10.1 2250.84    30.3 2236.49    40.4 2230.41    90.9 2202.02   141.4 2171.22
   151.5 2166.43   232.3 2138.28   252.5 2131.75   282.8  2122.8     303 2117.89
   333.3 2112.72   353.5 2106.94   363.6 2105.08   383.6 2104.85   393.5 2103.78
   403.5 2101.17   413.4 2097.89   443.2 2086.94   455.6 2085.31   463.1 2085.24
   470.6 2086.02   502.9 2091.25   512.8 2093.52   522.8 2097.02   582.4 2121.85
   601.7 2128.46   630.7 2136.93   659.6 2142.99   727.2 2153.38   785.1  2164.2
#Mann= 3 , 0 , 0
       0     .08       0   455.6    .045       0   470.6     .08       0
Bank Sta=455.6,470.6
XS Rating Curve= 0 ,0
Exp/Cntr=0.3,0.1

Type RM Length L Ch R = 1 ,4286.3  ,388.1,373.7,358.2
XS GIS Cut Line= 4
     1860773.274      143075.974     1860814.989      143397.509
     1860781.332      143569.159     1860831.817      143861.975
#Sta/Elev= 30
     9.8 2274.53    39.3 2248.07    49.1 2239.79      59 2232.73   127.7 2187.34
   157.2 2168.56     167 2163.05   176.9 2158.39   206.3 2146.07   255.5 2126.29
   275.1 2118.91   294.8 2112.12   363.1 2090.42   392.3 2079.51     402 2076.48
   404.2 2076.29   411.7 2075.63   419.2 2075.83   450.6 2077.86   489.4 2081.69
   509.1 2084.48     519 2086.38   528.9 2089.82   538.8 2094.99   548.7 2101.12
   598.2 2133.77   657.6 2172.07     727 2213.89   776.5  2245.5   796.3 2258.95
#Mann= 3 , 0 , 0
       0     .08       0   404.2    .045       0   419.2     .08       0
Bank Sta=404.2,419.2
XS Rating Curve= 0 ,0
Exp/Cntr=0.3,0.1

Type RM Length L Ch R = 1 ,3912.6  ,396.1,400,402.4
XS GIS Cut Line= 3
     1860268.898      143204.322     1860443.735       143573.88
     1860639.147      143941.525
#Sta/Elev= 30
      10 2284.83    39.9 2259.68    59.8 2243.45    79.8 2228.09    89.7 2221.39
   139.6 2192.02   199.4 2157.87   219.4 2147.26   279.2  2121.4     359 2083.88
   378.9 2074.11   388.9 2068.57   398.9 2064.02   401.3 2063.62   408.8 2062.38
   416.3  2062.7   428.7 2064.17     498 2074.23     508 2076.75   517.9 2080.78
   527.8 2085.56   547.6 2096.12   597.2  2125.3   626.9 2141.61   676.5 2166.33
   696.3 2175.19     736 2191.71   765.7 2205.59   785.5 2216.24   825.2 2239.56
#Mann= 3 , 0 , 0
       0     .08       0   401.3    .045       0   416.3     .08       0
Bank Sta=401.3,416.3
XS Rating Curve= 0 ,0
Exp/Cntr=0.3,0.1