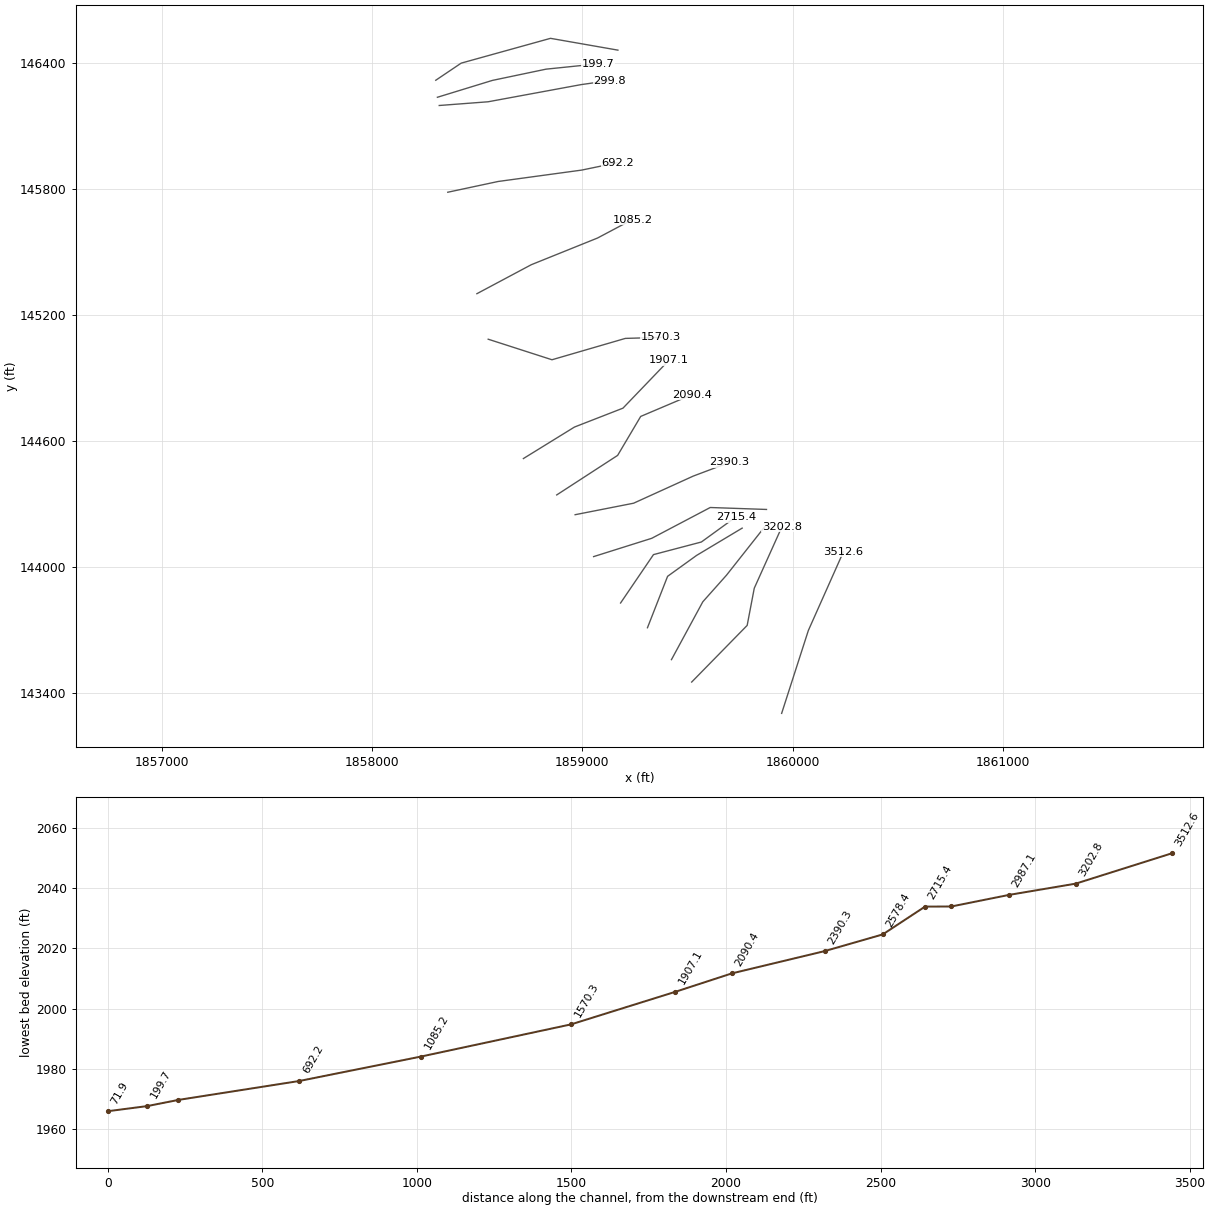
HEC-RAS study Leftwich Branch.prj: Leftwich Branch

--- Leftwich Branch.g01 (geometry) --- (continued)

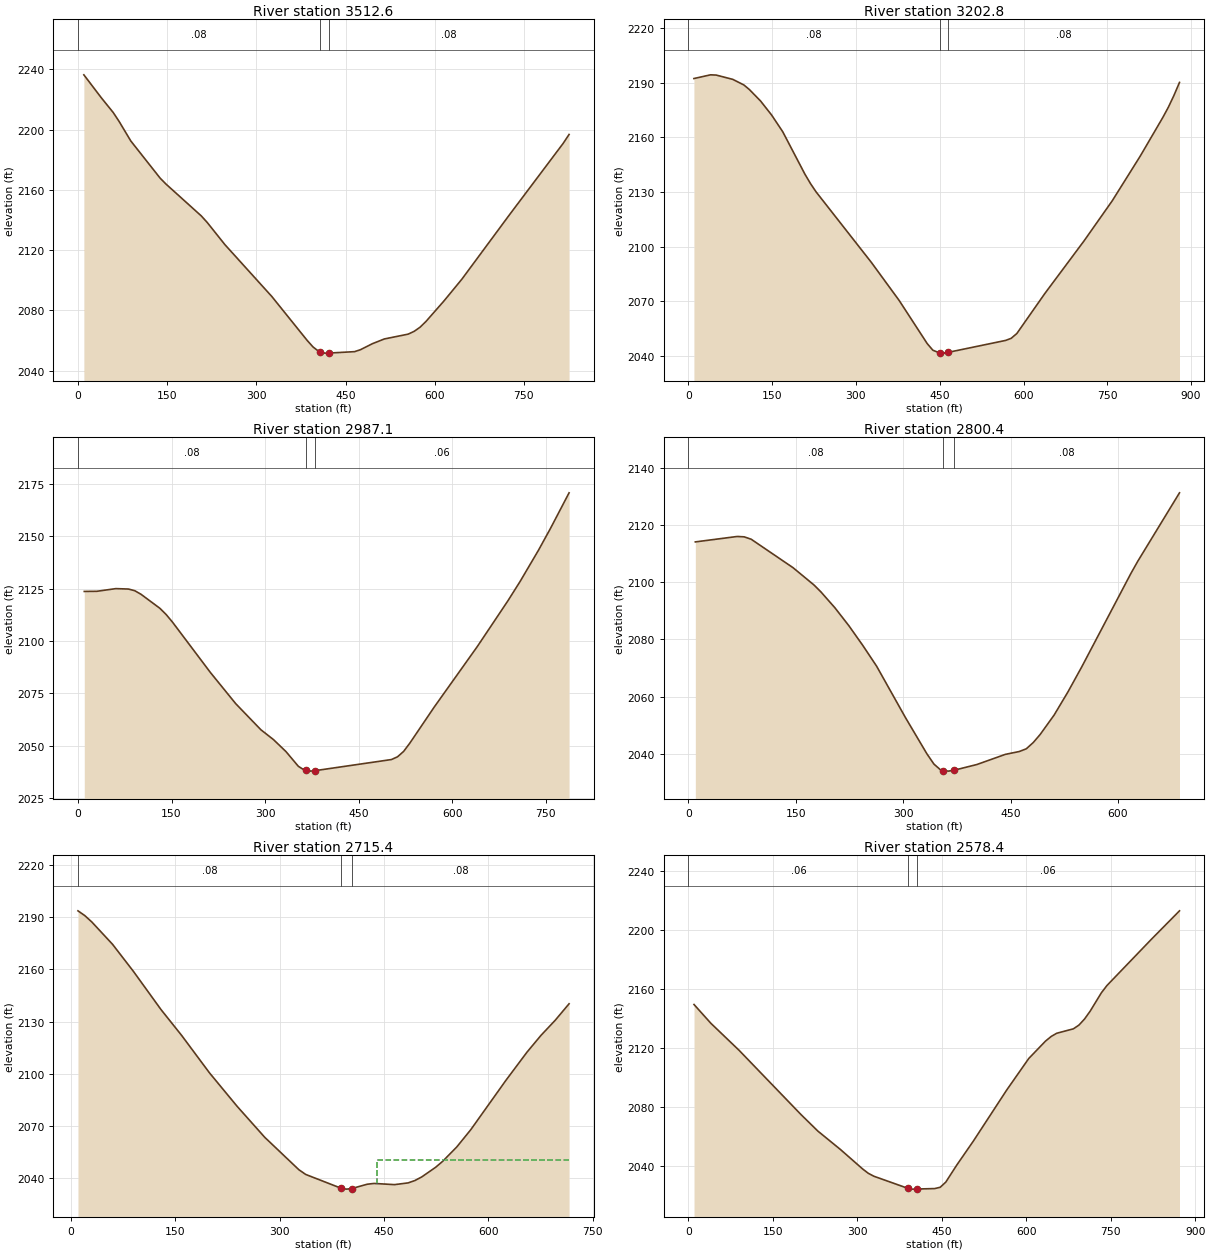
Type RM Length L Ch R = 1 ,3512.6  ,307.5,309.9,314.1
XS GIS Cut Line= 3
     1859947.568      143300.679     1860074.628      143695.796
     1860241.623      144071.314
#Sta/Elev= 30
     9.9 2236.38    39.5 2221.02    59.3 2211.35    69.2 2205.43    88.9 2192.44
   138.3 2167.73   148.2 2163.78   207.5 2142.66   217.4 2138.34   247.1 2123.64
   326.1 2089.16   385.4 2060.07   395.3 2055.69   405.2 2052.68   407.5 2052.42
     415 2051.58   422.5 2051.62   465.2 2052.56   475.2 2053.86   495.2 2057.84
   515.3 2060.99   555.4 2064.19   565.4 2066.04   575.4  2068.8   585.4 2072.65
   615.5 2086.19   645.6 2100.64   725.8 2143.48     816 2190.83     826 2196.79
#Mann= 3 , 0 , 0
       0     .08       0   407.5    .045       0   422.5     .08       0
Bank Sta=407.5,422.5
XS Rating Curve= 0 ,0
Exp/Cntr=0.3,0.1

Type RM Length L Ch R = 1 ,3202.8  ,227.5,215.7,204.4
XS GIS Cut Line= 4
     1859519.684      143449.953     1859783.601      143719.899
      1859817.36      143897.131     1859949.069      144190.205
#Sta/Elev= 30
     9.9 2192.23    39.7 2194.27    49.7 2194.14    79.5 2191.78    99.3 2188.72
   109.3 2186.17   129.2 2179.92     149 2172.21   168.9 2163.05   208.6 2139.78
   218.6 2134.59   228.5 2130.08   327.8 2091.25   377.5 2070.38   427.6 2046.77
   437.7 2043.14   450.2 2041.56   457.7 2041.53   465.2 2041.96     568  2048.5
     578 2049.67   588.1  2052.3   638.3 2074.29   708.6 2103.21   758.8 2125.09
     809 2149.65   849.1 2170.68   859.2 2176.39   869.2 2182.85   879.3  2190.1
#Mann= 3 , 0 , 0
       0     .08       0   450.2    .045       0   465.2     .08       0
Bank Sta=450.2,465.2
XS Rating Curve= 0 ,0
Exp/Cntr=0.3,0.1

Type RM Length L Ch R = 1 ,2987.1  ,191.6,186.7,182
XS GIS Cut Line= 4
     1859423.511      143556.734     1859572.611      143832.427
     1859685.139      143959.022     1859873.624      144198.144
#Sta/Elev= 30
    10.1 2123.61    30.3 2123.67    60.7 2124.95    80.9 2124.75      91 2123.96
   101.1 2122.24   131.4 2115.53   141.5 2112.54   151.7 2108.89   212.3  2084.9
   252.8 2070.04   293.2 2057.56   313.4 2052.85   333.4 2047.14   353.3 2040.09
   363.2 2038.23   365.7 2038.12   373.2 2037.79   380.7 2038.04   502.5 2043.32
   512.3 2044.63   522.1 2047.22   531.9 2051.11   571.2 2068.42     640 2097.21
   689.1 2119.07   708.7 2128.33   738.2 2143.26   757.8 2153.88   787.3  2170.7
#Mann= 3 , 0 , 0
       0     .08       0   365.7    .045       0   380.7     .06       0
Bank Sta=365.7,380.7
XS Rating Curve= 0 ,0
Exp/Cntr=0.3,0.1

Type RM Length L Ch R = 1 ,2800.4  ,93.2,84.9,76.7
XS GIS Cut Line= 4
     1859309.407      143708.796     1859405.112      143953.801
     1859542.928      144053.335     1859759.859      144183.494
#Sta/Elev= 30
     9.7 2114.03    68.2 2115.93    77.9  2115.8    87.7 2114.97   146.1 2105.04
   175.4 2098.99   185.1 2096.57   204.6 2091.04   224.1 2084.77   243.6 2077.87
     263 2070.58     303 2052.74     333 2040.06     343  2036.4     353 2034.21
   355.5 2034.14     363 2033.94   370.5 2034.21     403 2036.25   442.8  2039.8
   462.2 2040.79     472 2041.74   481.7 2043.92   491.4 2046.75   510.9 2053.54
   530.3 2061.67   549.8 2070.52   617.9 2102.91   627.6 2107.22     686 2131.18
#Mann= 3 , 0 , 0
       0     .08       0   355.5    .045       0   370.5     .08       0
Bank Sta=355.5,370.5
XS Rating Curve= 0 ,0
Exp/Cntr=0.3,0.1

Type RM Length L Ch R = 1 ,2715.4  ,129.8,137,142.3
XS GIS Cut Line= 4
       1859181.5      143826.699     1859337.984      144057.234
     1859565.724      144117.313     1859729.194      144236.073
#Sta/Elev= 30
      10 2193.51    19.9 2190.75    29.9 2187.12    59.7 2174.32    89.6 2158.86
   129.4 2136.88   159.2 2121.99     199 2100.64   238.8 2081.42   278.6 2063.61
   327.7 2045.01   337.5 2042.32   388.9 2034.33   396.4  2033.9   403.9 2034.25
   425.8  2036.7   435.6 2037.16   465.1 2036.48   484.7 2037.47   494.5 2038.83
   504.3 2040.89   524.3 2046.42   534.4 2049.84   554.6 2058.04   574.8 2067.96
   625.3 2096.25   655.6 2112.41   675.8 2122.08     696 2130.63   716.2  2140.2
#Mann= 3 , 0 , 0
      10     .08       0   388.9    .045       0   403.9     .08       0
#XS Ineff= 2 , 0
                          439.84         2050.32
Permanent Ineff=
       F       F
Bank Sta=388.9,403.9
XS Rating Curve= 0 ,0
Exp/Cntr=0.3,0.1

Type RM Length L Ch R = 1 ,2578.4  ,187.7,188.1,188.5
XS GIS Cut Line= 4
     1859053.296      144047.749     1859329.824      144135.003
     1859608.007      144281.751     1859875.528      144272.465
#Sta/Elev= 30
      10 2149.79      40 2137.03      90 2118.76     200 2075.19     230 2063.98
     270 2051.53   309.6 2038.28   319.5 2035.39   329.3 2033.41   390.6 2025.08
   398.1 2024.65   405.6 2024.72   437.4 2025.02   447.2  2025.9   457.1 2029.39
   476.7 2040.98   506.2 2057.27   565.2 2091.74   604.5 2113.19   634.2 2124.96
   644.1 2128.06   654.1 2130.29   683.8  2133.3   693.7 2135.86   703.6 2139.96
   713.5 2145.25   733.4 2157.68   743.3 2162.63   822.6 2194.11   872.2 2213.28
#Mann= 3 , 0 , 0
       0     .06       0   390.6    .045       0   405.6     .06       0
Bank Sta=390.6,405.6
XS Rating Curve= 0 ,0
Exp/Cntr=0.3,0.1

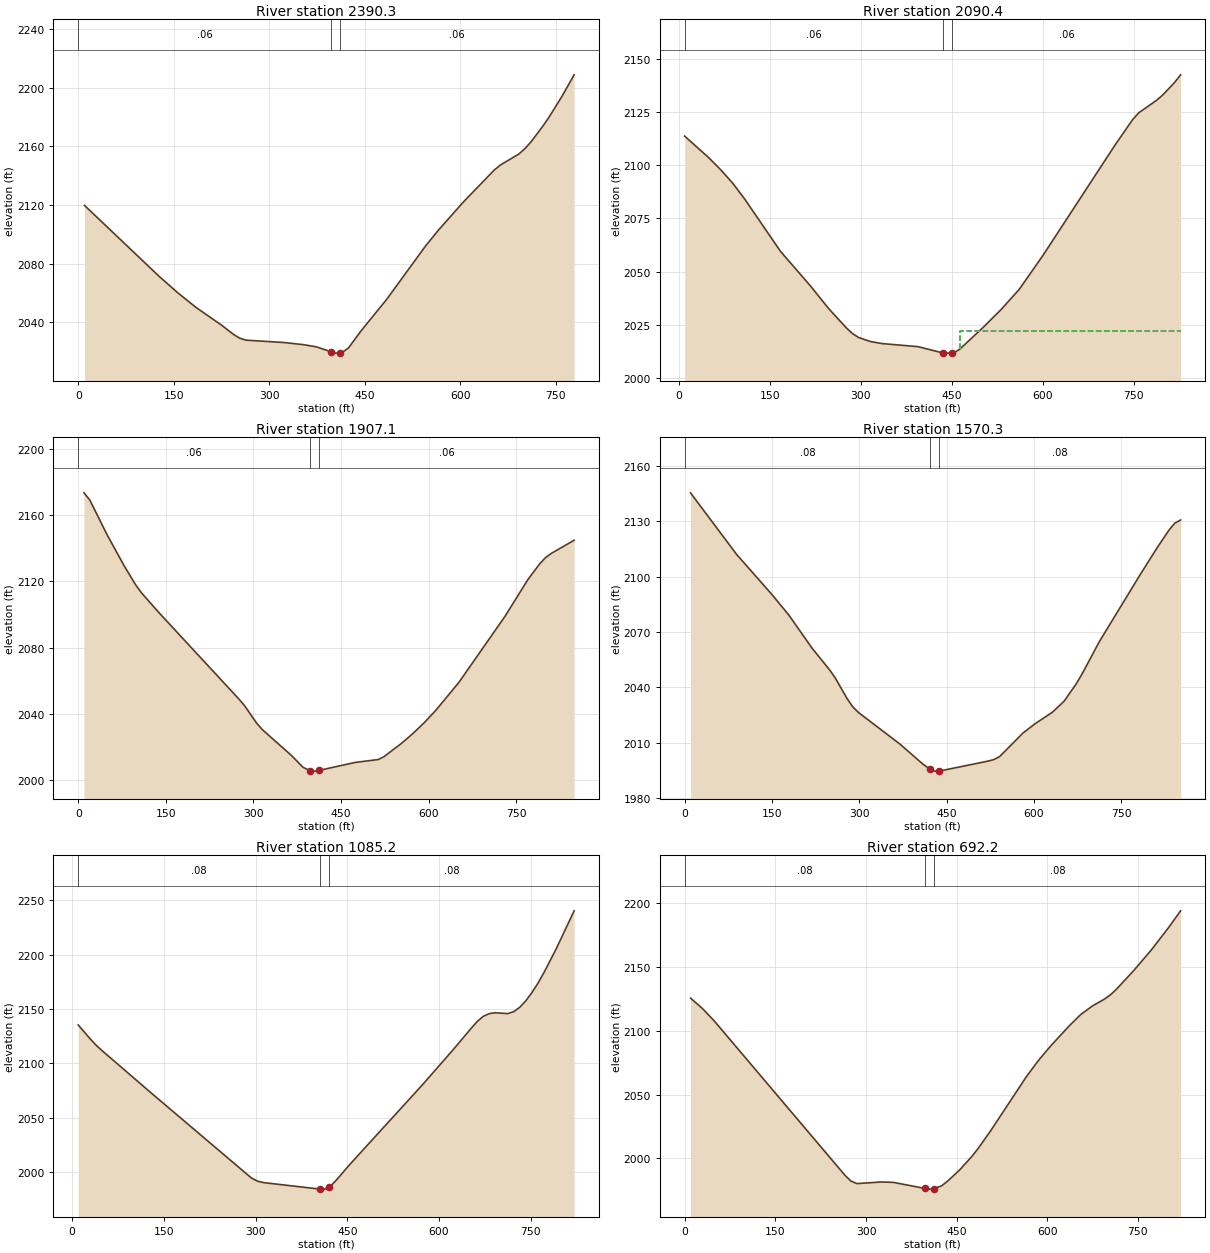
Type RM Length L Ch R = 1 ,2390.3  ,286,300,313.9
XS GIS Cut Line= 4
     1858965.402      144247.449     1859243.466      144302.233
       1859527.6       144431.64     1859699.205      144496.344
#Sta/Elev= 30
     9.8 2119.75     127 2071.44   156.4 2060.19   185.7 2050.01   224.8 2038.28
   244.3 2031.74   254.1  2029.2   263.9 2027.93   323.7  2026.3   353.9 2024.86
   374.1 2023.39   396.8 2020.06   404.3  2019.1   411.8 2019.35   414.3 2019.43
   424.4 2022.57   444.6 2034.44   484.8 2055.87   545.3  2091.9   565.4 2102.66
   605.3 2122.18   653.5 2143.81   663.2 2147.23   692.2 2154.72   701.8 2158.45
   711.5 2163.11   730.8 2174.27   740.4  2180.4   759.7 2193.88     779 2208.65
#Mann= 3 , 0 , 0
       0     .06       0   396.8    .045       0   411.8     .06       0
Bank Sta=396.8,411.8
XS Rating Curve= 0 ,0
Exp/Cntr=0.3,0.1

Type RM Length L Ch R = 1 ,2090.4  ,199,183.3,167.6
XS GIS Cut Line= 4
      1858877.75      144341.617      1859167.51      144530.102
     1859277.225      144715.774     1859521.973      144819.862
#Sta/Elev= 30
     9.9 2113.65    49.4 2103.55    69.1  2097.9    88.9  2091.6   108.6 2084.18
   167.9 2059.49   217.3 2043.24   246.9 2032.73   276.5 2023.52   286.4 2020.91
   296.3 2019.08     316 2017.15   335.8 2016.17   394.7 2014.74   436.2 2011.73
   443.7  2011.7   451.2 2011.78   453.5  2011.8   463.3 2013.57   502.5 2023.96
   531.9 2032.33   561.3 2041.65   600.7 2057.71   718.9 2109.32   748.5 2121.52
   758.3 2124.58   787.9 2130.53   797.7 2132.94   817.4 2138.86   827.3 2142.44
#Mann= 3 , 0 , 0
     9.9     .06       0   436.2    .045       0   451.2     .06       0
#XS Ineff= 2 , 0
                          463.27         2022.24
Permanent Ineff=
       F       F
Bank Sta=436.2,451.2
XS Rating Curve= 0 ,0
Exp/Cntr=0.3,0.1

Type RM Length L Ch R = 1 ,1907.1  ,338.8,336.7,334.8
XS GIS Cut Line= 4
     1858719.328      144515.038     1858962.146      144665.136
     1859192.828      144755.158     1859411.271      144983.068
#Sta/Elev= 30
     9.8 2173.48    19.7 2169.23    49.2 2148.35    78.7  2129.4    98.4 2117.92
   108.3 2113.15   137.8 2101.33   275.6 2048.84   285.5 2044.68   305.3 2034.55
   315.2 2030.58   364.7  2015.1   384.5 2007.95   396.8 2005.76   404.3 2005.56
   411.8 2005.96   473.7 2010.79   513.3 2012.54   523.2 2014.24   552.8 2022.19
   572.6 2028.19   592.3 2034.81     612 2042.22   651.5 2059.08   730.4 2098.93
   769.9 2121.28   789.6 2130.52   799.5 2134.28   809.3 2136.85   848.8 2144.87
#Mann= 3 , 0 , 0
       0     .06       0   396.8    .045       0   411.8     .06       0
Bank Sta=396.8,411.8
XS Rating Curve= 0 ,0
Exp/Cntr=0.3,0.1

Type RM Length L Ch R = 1 ,1570.3  ,483,485.2,487.2
XS GIS Cut Line= 4
     1858551.928      145083.732     1858855.244      144985.841
      1859204.23      145087.598     1859373.899      145092.494
#Sta/Elev= 30
      10 2145.25    89.6  2111.8   149.4 2090.45   179.3    2079   219.1 2061.14
     249 2049.52     259 2044.99   278.9 2034.05   288.8 2029.54   298.8  2026.4
   369.2 2009.54   409.6 1998.47   422.3 1995.66   429.8 1994.76   437.3 1994.78
   520.7 2000.15   530.8 2000.97   540.9 2002.58   581.3 2015.39   601.5 2020.28
   631.8 2026.63   651.9  2032.6   672.1 2041.68   682.2 2047.02   712.2 2064.68
   782.1 2100.79     812 2115.72     832 2125.08     842 2128.83     852 2130.57
#Mann= 3 , 0 , 0
       0     .08       0   422.3    .045       0   437.3     .08       0
Bank Sta=422.3,437.3
XS Rating Curve= 0 ,0
Exp/Cntr=0.3,0.1

Type RM Length L Ch R = 1 ,1085.2  ,398.6,393,387.3
XS GIS Cut Line= 4
     1858498.124      145300.631     1858756.782      145438.767
     1859071.767      145565.866     1859237.779      145654.011
#Sta/Elev= 30
    10.1 2135.21    30.3 2122.02    40.4    2116    50.6 2110.84   131.4 2071.65
   293.2 1994.35   303.2 1991.41   313.2 1990.07   405.6 1984.08   413.1 1984.07
   420.6 1986.25   423.1 1986.97   433.1 1993.01   453.1 2006.15     573  2080.2
   622.9  2112.3   652.7 2132.23   662.6 2138.47   672.5  2143.2   682.4 2145.69
   692.2 2146.47     712 2145.64   721.9 2147.39   731.8 2151.39   741.7 2157.31
   751.6 2164.86   761.5 2173.42   771.4 2183.27   791.2 2204.89   820.9 2240.28
#Mann= 3 , 0 , 0
    10.1     .08       0   405.6    .045       0   420.6     .08       0
Bank Sta=405.6,420.6
XS Rating Curve= 0 ,0
Exp/Cntr=0.3,0.1

Type RM Length L Ch R = 1 ,692.2   ,391.4,392.4,393.4
XS GIS Cut Line= 4
     1858359.615      145784.137     1858599.242      145835.429
     1858996.331      145889.632     1859167.492      145925.122
#Sta/Elev= 30
     9.8  2125.5    29.4 2117.38      49 2107.65   265.1 1986.87   275.1 1982.28
   285.1  1980.3   325.2 1981.55   345.2 1981.26   397.9 1976.48   405.4 1975.96
   412.9 1976.26   425.4 1978.63   435.4 1982.33   455.5 1991.23   475.5 2001.76
   485.5 2007.76   505.6 2021.18   565.7 2064.21   585.7 2076.93   605.7 2088.13
   635.8 2103.59   655.5 2112.78     675  2119.5   694.4 2124.73   704.1 2127.97
   713.8  2132.2   742.9 2147.06   772.1 2163.25   801.2  2181.1   820.6  2193.9
#Mann= 3 , 0 , 0
       0     .08       0   397.9    .045       0   412.9     .08       0
Bank Sta=397.9,412.9
XS Rating Curve= 0 ,0
Exp/Cntr=0.3,0.1

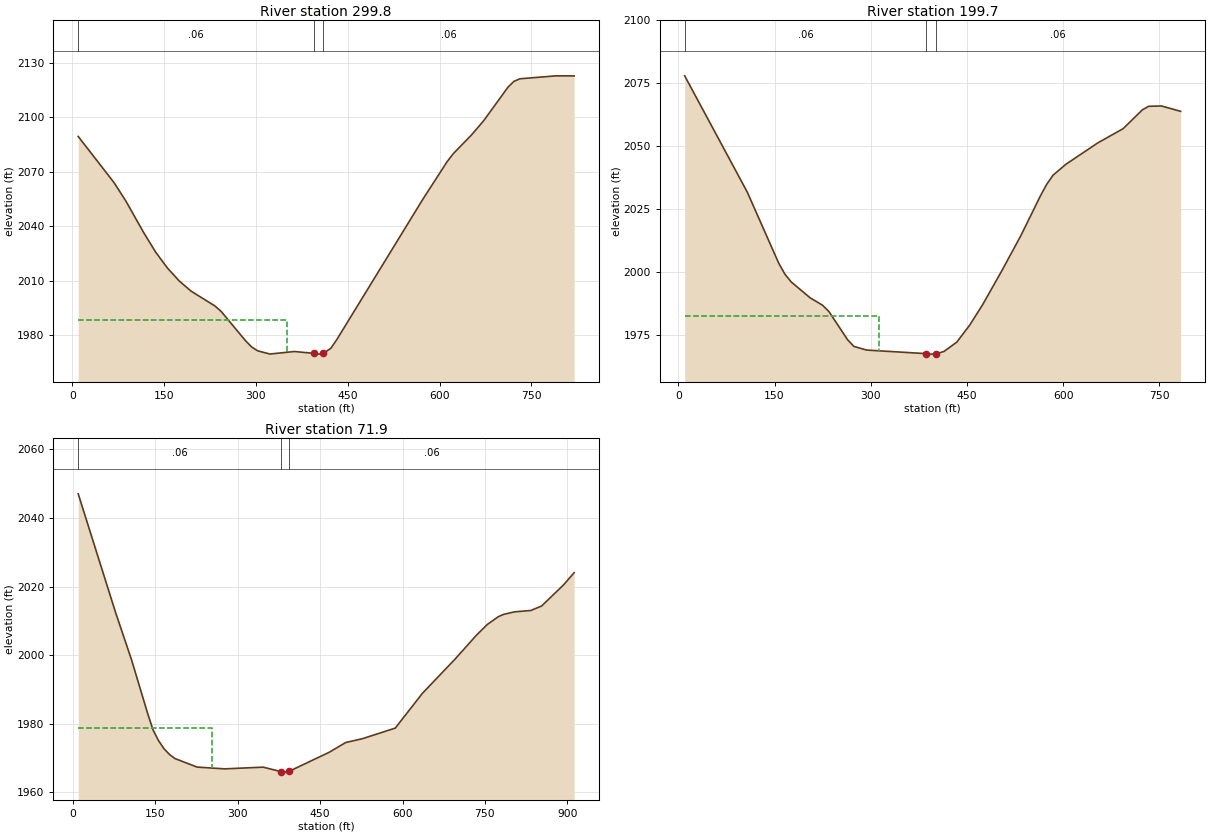
Type RM Length L Ch R = 1 ,299.8   ,99.5,100.1,100.6
XS GIS Cut Line= 4
     1858319.013       146197.52     1858551.418      146215.211
     1858993.077       146296.89     1859129.522      146316.293
#Sta/Elev= 30
     9.7 2089.44      68 2064.14    87.4    2054   116.5 2036.62     136  2025.9
   155.4 2017.06   174.8  2009.9   194.2 2004.29   233.1 1996.15   243.1 1993.22
     283 1977.06     293 1973.62   302.9 1971.47   322.9  1969.7   362.8 1971.09
   395.3 1970.07   402.8 1969.65   410.3 1970.04   422.7 1972.94   432.7 1977.93
   572.4 2054.66   612.4 2075.53   622.3 2079.87   652.3 2090.26   672.2 2098.09
   711.8 2116.51   721.6 2119.75   731.4 2121.16   790.5 2122.79     820 2122.75
#Mann= 3 , 0 , 0
     9.7     .06       0   395.3    .045       0   410.3     .06       0
#XS Ineff= 2 , 0
          350.02 1988.47
Permanent Ineff=
       F       F
Bank Sta=395.3,410.3
XS Rating Curve= 0 ,0
Exp/Cntr=0.3,0.1

Type RM Length L Ch R = 1 ,199.7   ,126.4,127.8,129.3
XS GIS Cut Line= 4
     1858310.245      146236.688     1858571.839       146317.08
     1858827.053      146370.675      1859074.61      146396.196
#Sta/Elev= 30
     9.8 2077.94   107.5 2031.81   156.4  2003.7   166.2 1999.29   175.9 1996.24
   205.3 1989.97   224.8    1987   234.6 1984.56   263.9 1973.31   273.7 1970.67
   293.7 1969.22   386.5  1967.8     394 1967.61   401.5 1967.71   414.1 1968.66
   434.1 1972.34   454.2 1979.06   474.3 1987.12   504.4 2000.64   534.4 2014.72
   564.3 2030.18   574.3 2034.87   584.2 2038.51   604.1 2042.82   653.9 2051.32
   693.7    2057   723.6 2064.45   733.5 2065.86   753.5 2065.99   783.3 2063.86
#Mann= 3 , 0 , 0
     9.8     .06       0   386.5    .045       0   401.5     .06       0
#XS Ineff= 2 , 0
          313.46 1982.91
Permanent Ineff=
       F       F
Bank Sta=386.5,401.5
XS Rating Curve= 0 ,0
Exp/Cntr=0.3,0.1

Type RM Length L Ch R = 1 ,71.9    ,72.8,71.9,71
XS GIS Cut Line= 4
     1858302.478      146317.808     1858423.445      146399.391
     1858848.239      146517.546     1859168.944      146461.282
#Sta/Elev= 30
     9.7 2047.01    77.8 2012.39     107 1998.52   136.2 1982.94   145.9 1978.21
   155.9 1975.08   165.9 1972.71     176 1971.03     186 1969.84   226.1 1967.37
   276.2 1966.85   346.3 1967.35   378.9 1966.05   386.4  1965.9   393.9 1966.16
   466.6 1971.69   496.6 1974.53   526.7 1975.63   586.8 1978.73   636.2 1988.86
   695.4  1998.8   734.8 2005.85   754.6 2008.97   774.3 2011.19   784.2 2011.89
   803.9 2012.61   833.5 2013.01   853.2 2014.32   892.7 2020.41   912.4 2024.03
#Mann= 3 , 0 , 0
     9.7     .06       0   378.9    .045       0   393.9     .06       0
#XS Ineff= 2 , 0
          253.38 1978.78
Permanent Ineff=
       F       F
Bank Sta=378.9,393.9
XS Rating Curve= 0 ,0
Exp/Cntr=0.3,0.1

Chan Stop Cuts=-1
Use User Specified Reach Order=0